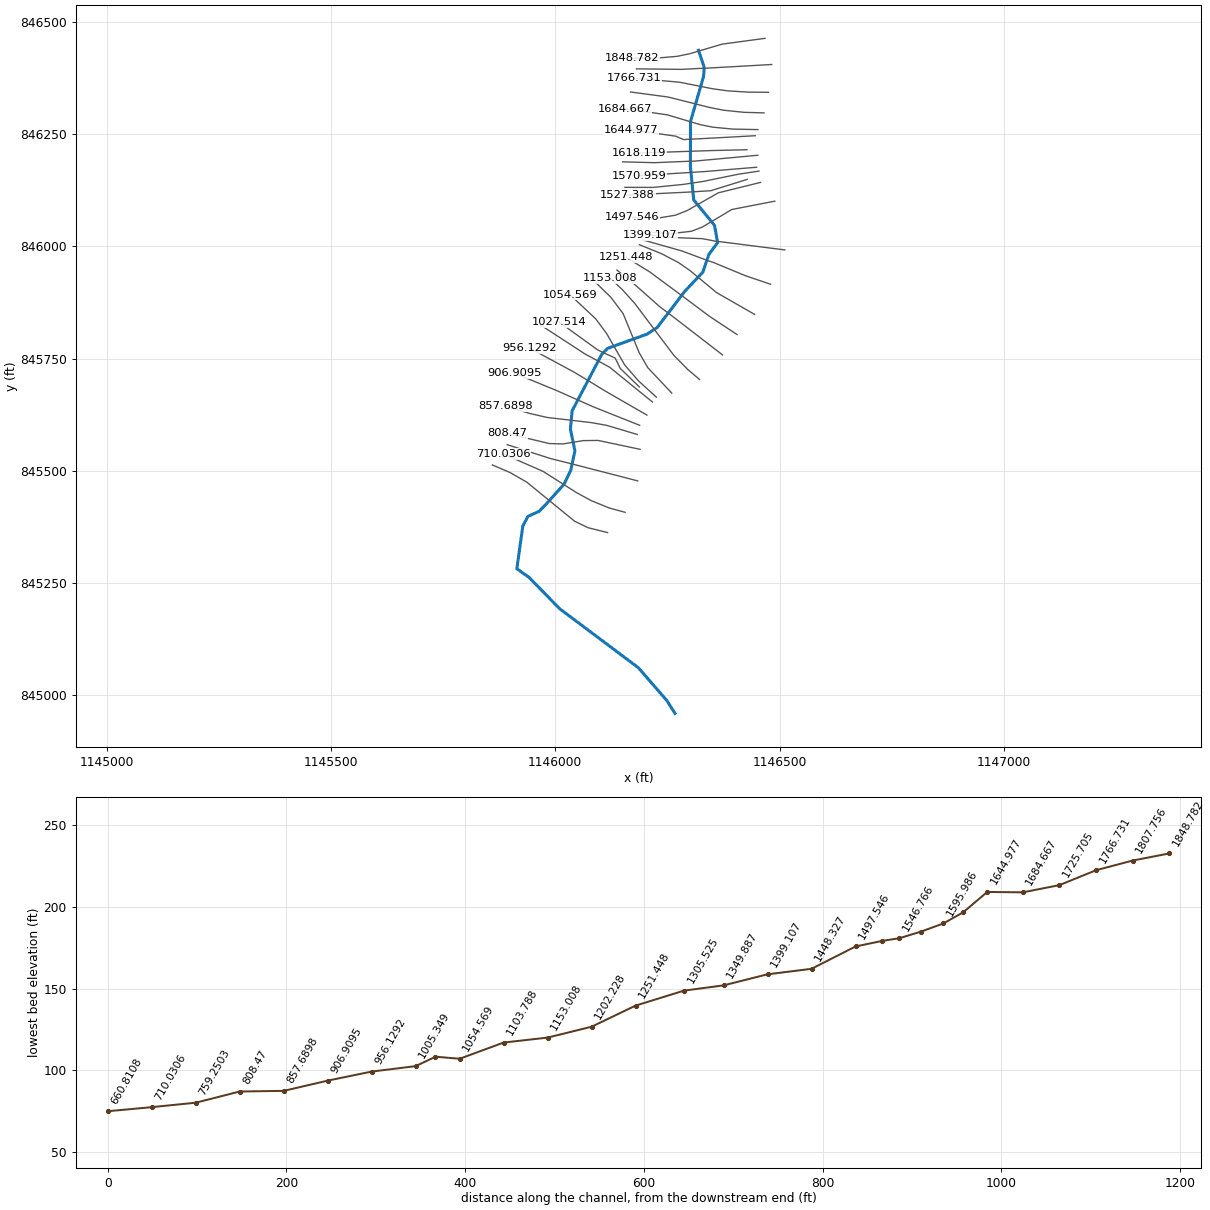
--- 9_ras.prj (project) ---

Proj Title=9
Current Plan=p01
Default Exp/Contr=0.3,0.1
English Units
Geom File=g01
Flow File=f01
Plan File=p01
Y Axis Title=Elevation
X Axis Title(PF)=Main Channel Distance
X Axis Title(XS)=Station
BEGIN DESCRIPTION:
RFD model 9 exported to HEC-RAS
END DESCRIPTION:

--- 9_ras.p01 (plan) ---

Plan Title=Plan 01
Program Version=4.10
Short Identifier=Plan 01
Geom File=g01
Flow File=f01
Subcritical Flow
Calc Critical at every XS
Secant Critical Depth

--- 9_ras.f01 (steady flow) ---

Flow Title=Flow 01
Program Version=5.01
Number of Profiles= 5
Profile Names=10yr,25yr,50yr,100yr,500yr
River Rch & RM=9,37,1848.782
   97.42  172.36  243.96  328.93  574.88
River Rch & RM=9,37,1349.887
  101.18  179.16  253.78  342.47  599.92
River Rch & RM=9,37,1251.448
  112.42  199.54  283.28  383.18  675.56
River Rch & RM=9,37,1153.008
  116.79  207.46  294.76  399.06  705.18
River Rch & RM=9,37,1005.349
   122.4  217.64  309.53   419.5  743.41
River Rch & RM=9,37,906.9095
  137.93   245.9   350.6  476.45   850.5
River Rch & RM=9,37,  808.47
  141.65  252.68  360.47  490.16  876.37
River Rch & RM=9,37,660.8108
   146.6  261.72  373.63  508.45  910.98
River Rch & RM=9,37,562.3714
   149.7  267.37  381.86   519.9  932.67
Boundary for River Rch & Prof#=9,37,1
Up Type= 0
Dn Type= 2
Boundary for River Rch & Prof#=9,37,2
Up Type= 0
Dn Type= 2
Boundary for River Rch & Prof#=9,37,2
Up Type= 0
Dn Type= 2
Boundary for River Rch & Prof#=9,37,2
Up Type= 0
Dn Type= 2
Boundary for River Rch & Prof#=9,37,2
Up Type= 0
Dn Type= 2

--- 9_ras.g01 (geometry) ---

Geom Title=9
Program Version=4.10

River Reach=9,37
Reach XY= 30
1146319.27496964846437.0550562591146332.03587267846399.212378442
1146330.71577922846379.4109772591146301.51716113846278.501319468
1146301.23369306846177.4366852491146308.71422237 846103.51145418
1146354.91749179846047.1874686031146361.95798999846008.464728519
1146342.59661996845982.5028914361146328.95565468845942.460057899
 1146288.9128212845900.2170687321146227.30846199845819.251339465
1146205.30690509845804.7303119451146116.42061535845772.608038917
1146103.65971237845759.4071047751146037.65504178 845633.55819951
1146033.69476157845593.075334877 1146043.8154777845544.231878623
1146034.57482383845501.1088271891146019.61376515845469.866616443
1145980.01096278845425.8635026961145964.16984183845409.582350627
1145939.08806705845398.1415410341145927.64725745845376.580015332
 1145914.3917641845281.4732949141145941.38166663845262.306659982
1146010.40757996 845191.838779331146185.19959259845060.787769794
1146248.90592644844987.4292977151146266.86933106 844959.03917405

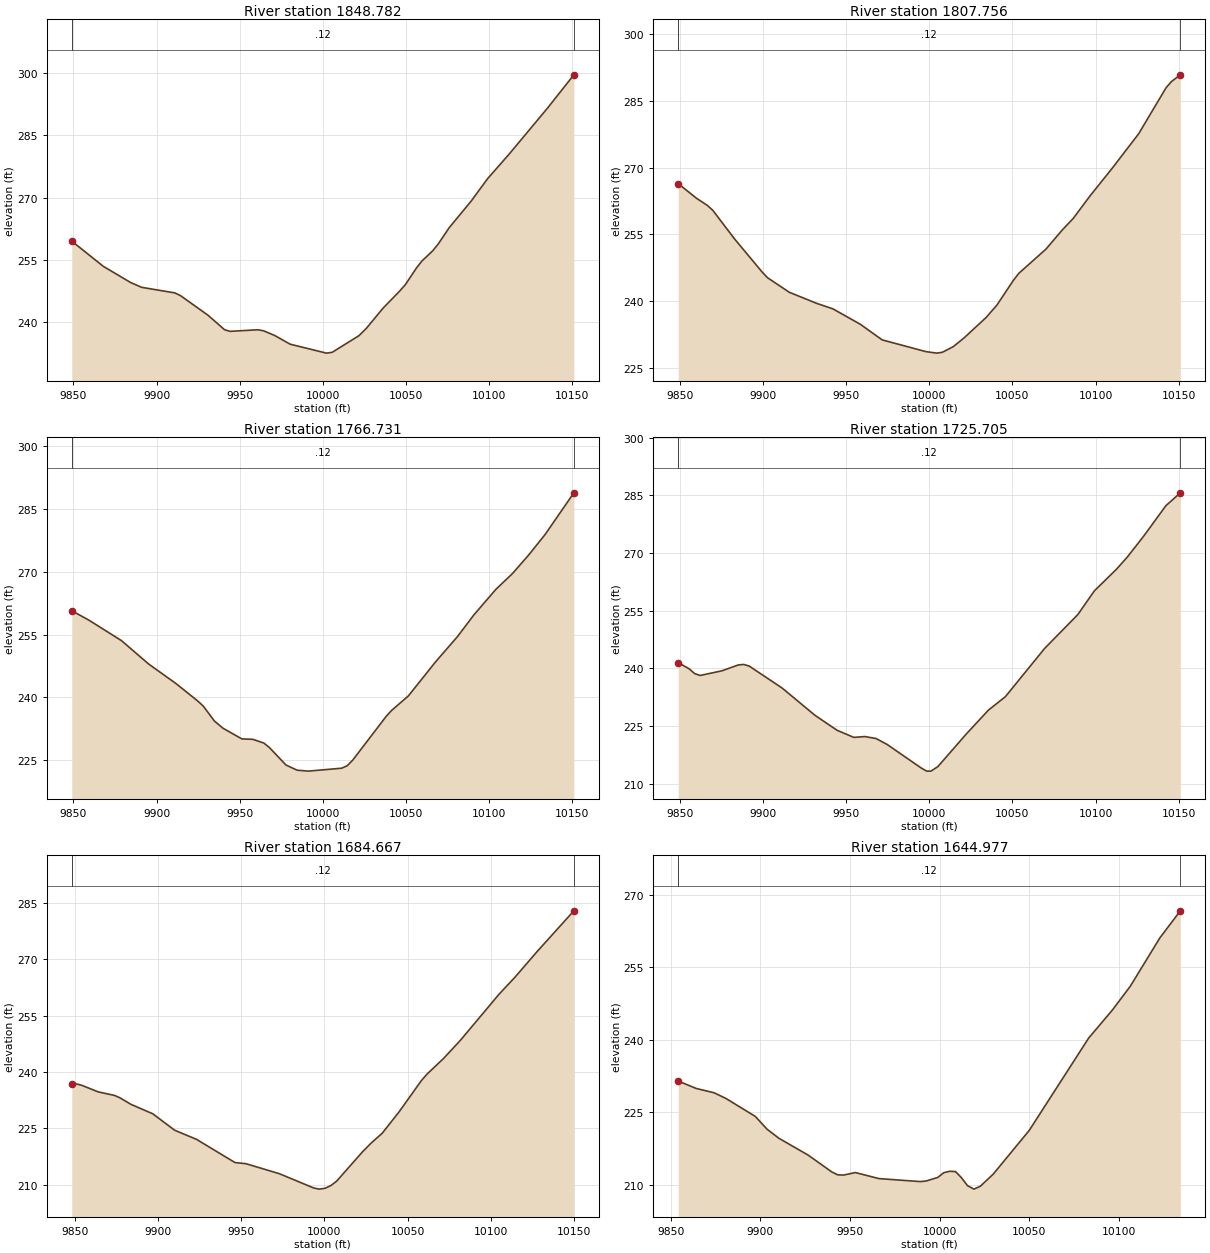
Type RM Length L Ch R = 1 ,1848.782,41.025600,41.025600,41.025600
XS GIS Cut Line= 6
 1146467.6101488846463.8323902461146372.22619055846450.924237408
1146298.92744566846429.3222621591146271.28209845846423.639874534
1146224.94630378 846419.726737131146170.51368126846419.286930341
#Sta/Elev= 30
9849.025259.53899867.977253.48589884.488249.58399891.092248.44119910.947247.1081
9914.272246.49049930.897241.76189940.872238.27419944.197237.87599961.066238.2535
9964.443237.99879971.198236.85489980.303 234.797 10002.2232.646310005.65 232.847
10021.79236.855810026.23 238.61810036.27243.465110046.32247.589310049.67 249.113
10056.26253.059910059.55254.741110066.14257.241410069.43258.863910076.02262.7748
10089.19269.139910099.06274.516810112.18280.490710135.15291.486810150.95299.4615
#Mann= 3 , 0 , 0
9849.025    0.12       09849.025    0.12       010150.95    0.12       0
#XS Ineff= 2 , 0
       0                               0
Bank Sta=9849.025,10150.95
Exp/Cntr=0.3,0.1

Type RM Length L Ch R = 1 ,1807.756,41.025600,41.025600,41.025600
XS GIS Cut Line= 5
 1146482.6519665846405.5008648381146332.89747419846397.103104913
1146330.90190387846397.236142938  1146281.941156846394.677728386
1146181.00427804 846395.80189288
#Sta/Elev= 30
 9849.01266.42989859.932263.15439866.504261.5349 9869.79260.42269882.934253.9626
9899.364246.5837 9902.65 245.2759915.794241.98059932.224239.49199942.082238.2417
9958.512234.78219971.656231.26669997.944228.626810004.52228.2859 10007.8228.4703
10014.37229.728110020.94231.720510034.08236.271110040.65239.082410050.51244.6231
10053.79246.2233 10070.2251.705110080.04256.0219 10086.6258.607510096.44263.5577
10109.57269.675810125.97277.671310142.38287.990910145.66289.402410150.97 290.911
#Mann= 3 , 0 , 0
 9849.01    0.12       0 9849.01    0.12       010150.97    0.12       0
#XS Ineff= 2 , 0
       0                               0
Bank Sta=9849.01,10150.97
Exp/Cntr=0.3,0.1

Type RM Length L Ch R = 1 ,1766.731,41.025600,41.025600,41.025600
XS GIS Cut Line= 6
1146475.40303336846343.5499199331146429.98670804846343.891383873
1146384.57203942846346.7363976611146350.99757246 846351.38194096
1146276.27346101846366.1387271051146175.70066877846374.821612487
#Sta/Elev= 30
9849.024260.69479859.242258.46579878.927253.54959895.333247.9429 9911.77243.2764
9924.919239.08639928.206237.87449934.781234.35849939.945232.63369951.302230.0743
9957.926229.9791 9964.55229.08089967.863228.02119977.848223.83429984.553 222.603
9991.259222.377910011.34223.077710014.68 223.67210018.02225.019610038.06235.4398
 10041.4236.893610051.39240.316310067.86248.508110081.03254.538210090.91259.7291
10104.08 265.80810113.96269.533210123.84 274.02910133.72278.927510150.96288.8614
#Mann= 3 , 0 , 0
9849.024    0.12       09849.024    0.12       010150.96    0.12       0
#XS Ineff= 2 , 0
       0                               0
Bank Sta=9849.024,10150.96
Exp/Cntr=0.3,0.1

Type RM Length L Ch R = 1 ,1725.705,41.038700,41.038700,41.038700
XS GIS Cut Line= 6
1146465.23815965846297.6346091911146420.36043778846298.924557787
1146374.85709404846303.6349171771146343.81051502846309.766270263
1146251.76542068846332.9748245041146167.81621364846344.225917758
#Sta/Elev= 30
9849.032241.49819855.649 239.8679858.931238.63249862.213238.14849875.342239.3677
9885.188240.89119888.471241.01249891.753240.58689911.532  234.879931.323227.7643
9944.583223.88279954.616222.03749961.304222.25089967.993221.74759974.724220.1796
9995.044214.1022 9998.43213.2573   10001213.255910005.19214.4383 10022.1222.8417
10035.63229.151110045.78232.6336 10069.4245.202310089.34253.9956 10099.3260.1759
10112.55265.783210119.15268.995110129.06274.477410142.26282.313410150.97285.6812
#Mann= 3 , 0 , 0
9849.032    0.12       09849.032    0.12       010150.97    0.12       0
#XS Ineff= 2 , 0
       0                               0
Bank Sta=9849.032,10150.97
Exp/Cntr=0.3,0.1

Type RM Length L Ch R = 1 ,1684.667,39.689700,39.689700,39.689700
XS GIS Cut Line= 6
1146451.56574561846260.4236207821146396.53685176846261.453484047
1146350.84573256846265.8202225321146323.18719732846271.447972715
1146249.70808211846293.3150108971146154.65297371846306.910086786
#Sta/Elev= 30
9848.047236.88539850.832 236.8649854.113236.47989863.957 234.7399873.802233.7887
9877.083233.14649883.646 231.4199896.771228.90489909.927224.5288 9923.11222.0882
 9946.18215.92569952.832215.6133 9972.92212.94889993.475 209.1649996.922208.8459
10000.39209.078410003.86209.792410007.32210.966110022.87218.769410027.97221.0624
10034.73 223.72610044.87229.414610058.33237.762610061.66239.454910071.64243.6439
10081.63248.404410104.86260.674510114.78265.3706   10128272.157710149.98282.9479
#Mann= 3 , 0 , 0
9848.047    0.12       09848.047    0.12       010149.98    0.12       0
#XS Ineff= 2 , 0
       0                               0
Bank Sta=9848.047,10149.98
Exp/Cntr=0.3,0.1

Type RM Length L Ch R = 1 ,1644.977,26.857900,26.857900,26.857900
XS GIS Cut Line= 5
 1146445.7536394846246.7115195691146344.77370271846241.203523025
1146286.02720389846238.1544745421146268.54664069846245.716987729
1146168.51781315846260.022511244
#Sta/Elev= 30
9854.159231.4712 9864.27229.92739874.127229.04969880.698227.87759897.127224.1563
9903.698 221.505 9910.27219.62949926.698 216.1179939.841212.64049943.127212.0437
9946.413 212.0039952.984212.51949966.125211.27059989.122210.65319992.407210.7684
9998.978211.523910002.26212.490110005.55212.789510008.83212.721410012.12211.4627
10015.52209.809310019.09209.089410022.67209.691410029.82212.179710049.95221.2523
10083.09240.367410096.34 246.18510106.29251.090810122.86261.146810134.21266.7217
#Mann= 3 , 0 , 0
9854.159    0.12       09854.159    0.12       010134.21    0.12       0
#XS Ineff= 2 , 0
       0                10013.94       0
Bank Sta=9854.159,10134.21
Exp/Cntr=0.3,0.1

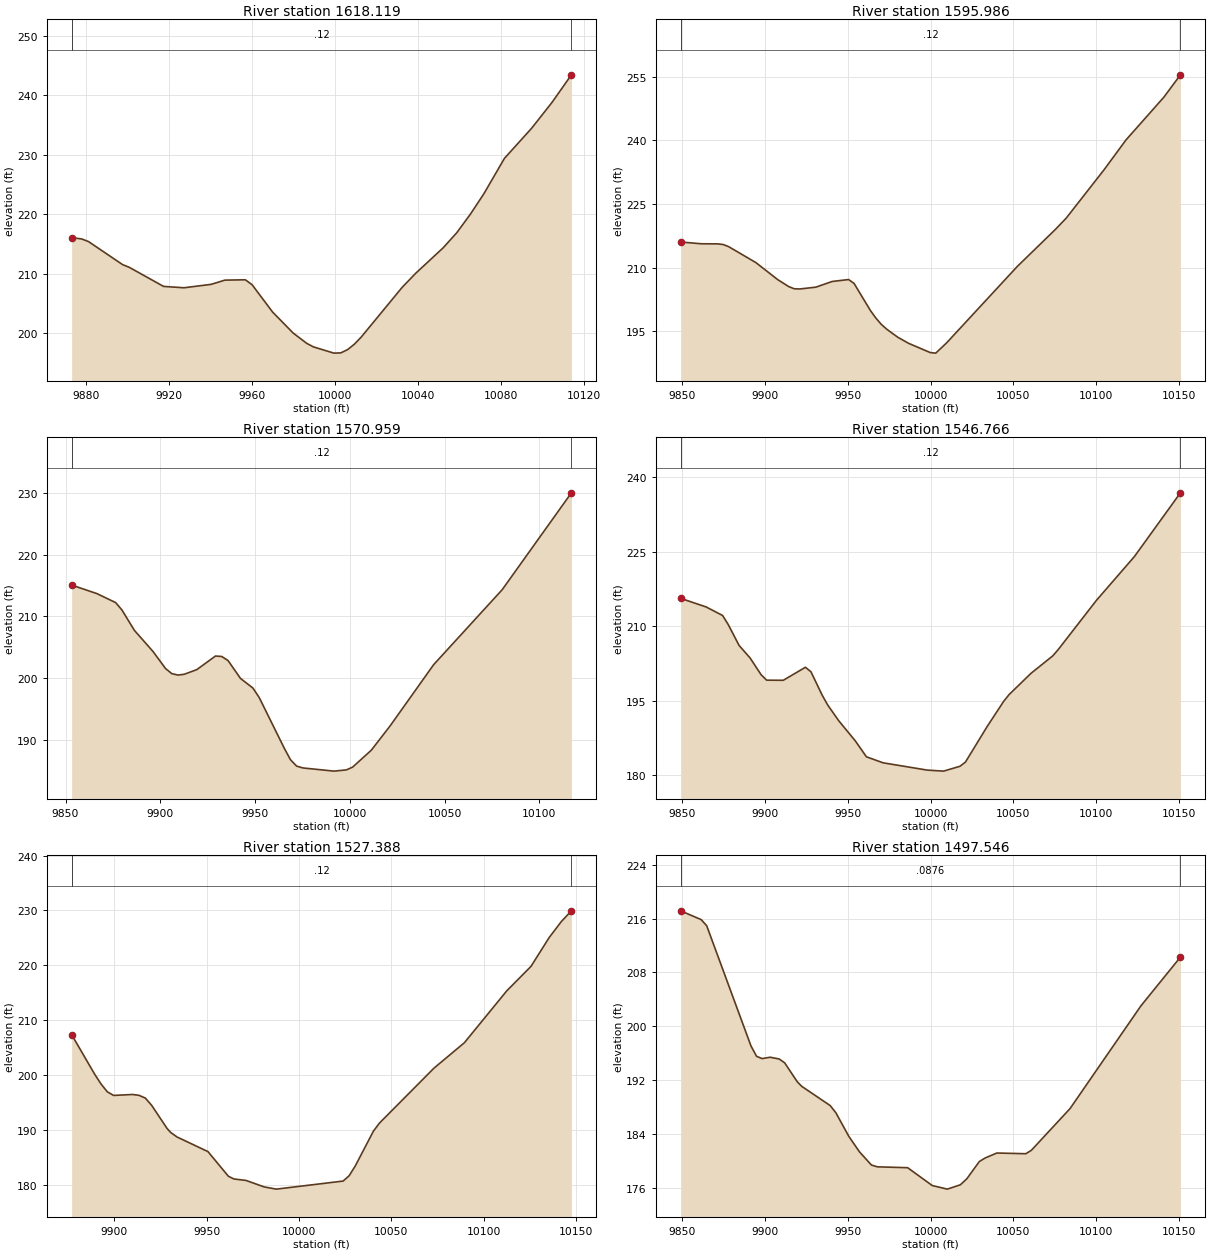
Type RM Length L Ch R = 1 ,1618.119,22.133200,22.133200,22.133200
XS GIS Cut Line= 3
1146427.39365095846215.4995391071146348.44570041846213.663540259
1146186.87780166846208.155543715
#Sta/Elev= 30
9873.153216.08129878.013215.85749881.295215.41139897.703211.53959900.985211.0743
9917.394207.88499927.239 207.6559940.366208.23299946.929208.93759956.776208.9958
9960.058208.15759969.907 203.5749979.755200.0627 9986.32198.32039989.603197.7156
9999.451196.673210002.73196.712910006.02197.2615 10009.3198.181310012.58199.3717
10032.28207.724310038.84210.099110051.98214.351610058.54216.886410065.11 220.005
10071.67223.472510081.52229.393610094.65234.4691 10104.5238.830210113.78243.4351
#Mann= 3 , 0 , 0
9873.153    0.12       09873.153    0.12       010113.78    0.12       0
#XS Ineff= 2 , 0
       0                               0
Bank Sta=9873.153,10113.78
Exp/Cntr=0.3,0.1

Type RM Length L Ch R = 1 ,1595.986,25.026900,25.026900,25.026900
XS GIS Cut Line= 6
1146451.38490217846203.1972219851146311.69450469846190.237545241
1146301.99830605846189.9216292311146299.99866195846189.883900094
1146221.20629222846186.6437464391146150.11578235846188.482793163
#Sta/Elev= 30
9849.008216.03659861.508215.62039871.393215.59899874.688215.44619877.983214.9488
9894.457211.18899907.637207.17889914.227205.55059917.522205.03259920.816 204.967
9930.701205.40039940.586206.74079950.471207.19469953.766206.2909 9963.65199.8999
9966.945198.1254 9970.24196.63169973.535195.49669980.125193.61729986.715192.1685
9999.855189.983410003.14189.8578 10009.7192.274410052.39210.275210075.38218.9838
10081.94221.650610104.92233.104110118.04240.063310141.02250.182710150.97255.4251
#Mann= 3 , 0 , 0
9849.008    0.12       09849.008    0.12       010150.97    0.12       0
#XS Ineff= 2 , 0
       0                               0
Bank Sta=9849.008,10150.97
Exp/Cntr=0.3,0.1

Type RM Length L Ch R = 1 ,1570.959,24.192900,24.192900,24.192900
XS GIS Cut Line= 3
1146448.96663743846176.4845635591146332.83971021846166.845569611
1146185.95980221846157.665575355
#Sta/Elev= 30
9853.235 215.0749866.589213.68439876.466212.22539879.758211.03489886.342207.7233
9896.218 204.2729902.802201.51539906.095200.69389909.387200.46199912.679200.5979
9919.263201.34899929.139203.55789932.432 203.4799935.724202.83229942.308199.9245
9948.892 198.3549952.184196.82869965.353188.63449968.645186.74959969.761 186.382
9971.934185.68939975.221 185.3929991.657184.87359998.232185.074110001.52185.5315
10011.38188.282910021.24192.202110044.25202.157410080.41214.322510116.93230.0452
#Mann= 3 , 0 , 0
9853.235    0.12       09853.235    0.12       010116.93    0.12       0
#XS Ineff= 2 , 0
       0                               0
Bank Sta=9853.235,10116.93
Exp/Cntr=0.3,0.1

Type RM Length L Ch R = 1 ,1546.766,19.378400,19.378400,19.378400
XS GIS Cut Line= 6
1146454.15214769846167.9221899751146407.63642429846160.832377949
 1146329.2015613846144.7859144341146285.91012922846138.286113603
1146218.29383722846131.5077527281146155.20614908846131.667191016
#Sta/Elev= 30
9849.012215.60999864.401213.87799874.357212.15729877.676210.37999884.313206.1305
9890.951203.61099897.602200.24249900.951199.13759910.997199.11299924.392201.7329
9927.741200.82659934.439196.16519937.787194.16949944.485190.98659954.531186.9142
9961.229183.71379971.275182.50559997.904181.035510007.85180.827810017.78181.8067
10021.08182.653210034.27189.850910044.16 194.87210047.46196.244410060.65200.5083
10073.84204.036310077.14205.306310100.15215.183510123.12224.010810150.95 236.851
#Mann= 3 , 0 , 0
9849.012    0.12       09849.012    0.12       010150.95    0.12       0
#XS Ineff= 2 , 0
       0                               0
Bank Sta=9849.012,10150.95
Exp/Cntr=0.3,0.1

Type RM Length L Ch R = 1 ,1527.388,29.841300,29.841300,29.841300
XS GIS Cut Line= 4
1146427.85265061846149.4035805461146346.60970157846124.158596352
1146294.74273404846120.9455983791146161.17381775846114.519602403
#Sta/Elev= 30
 9876.85207.34859889.289200.15069892.725 198.3679896.161196.92479899.596196.2609
9909.903196.43429913.338196.27929916.774195.7799 9920.21 194.4459928.593190.2172
9930.516189.49939933.952188.68069950.706186.01349961.762181.51959964.745181.0227
9971.319180.7565 9981.18179.56959987.755179.169710023.91180.640110027.19 181.614
10030.47183.371110040.33189.739310043.61191.214910073.17201.2471 10089.6205.8667
10112.59215.340710125.73219.811510135.58225.072310142.15227.980210147.61229.9361
#Mann= 3 , 0 , 0
 9876.85    0.12       0 9876.85    0.12       010147.61    0.12       0
#XS Ineff= 2 , 0
       0                               0
Bank Sta=9876.85,10147.61
Exp/Cntr=0.3,0.1

Type RM Length L Ch R = 1 ,1497.546,49.219700,49.219700,49.219700
XS GIS Cut Line= 6
1146457.67691045846142.6698572611146363.40995119846119.428603856
 1146294.4035461846080.1000072911146267.72980984846069.520568377
 1146226.8015718846062.7621707131146172.35227291846064.879185584
#Sta/Elev= 30
9849.103217.17419861.506215.86489864.848214.94519891.582 197.0529894.924195.5272
9898.266195.18379903.142195.38589908.564195.12779911.881194.55969919.496191.7415
9922.199191.05719939.396188.19299942.835 187.1179950.665183.60119957.079181.3085
9964.284179.34569967.887179.07699986.168178.9461   10001 176.29310010.11175.7585
10017.99176.404810021.93 177.30610029.42179.860710032.95180.3914   10040181.1315
10057.52181.027110060.89181.543110084.23187.750110126.97203.017610150.86210.2892
#Mann= 3 , 0 , 0
9849.103  0.0876       09849.103  0.0876       010150.86  0.0876       0
#XS Ineff= 2 , 0
       0                               0
Bank Sta=9849.103,10150.86
Exp/Cntr=0.3,0.1

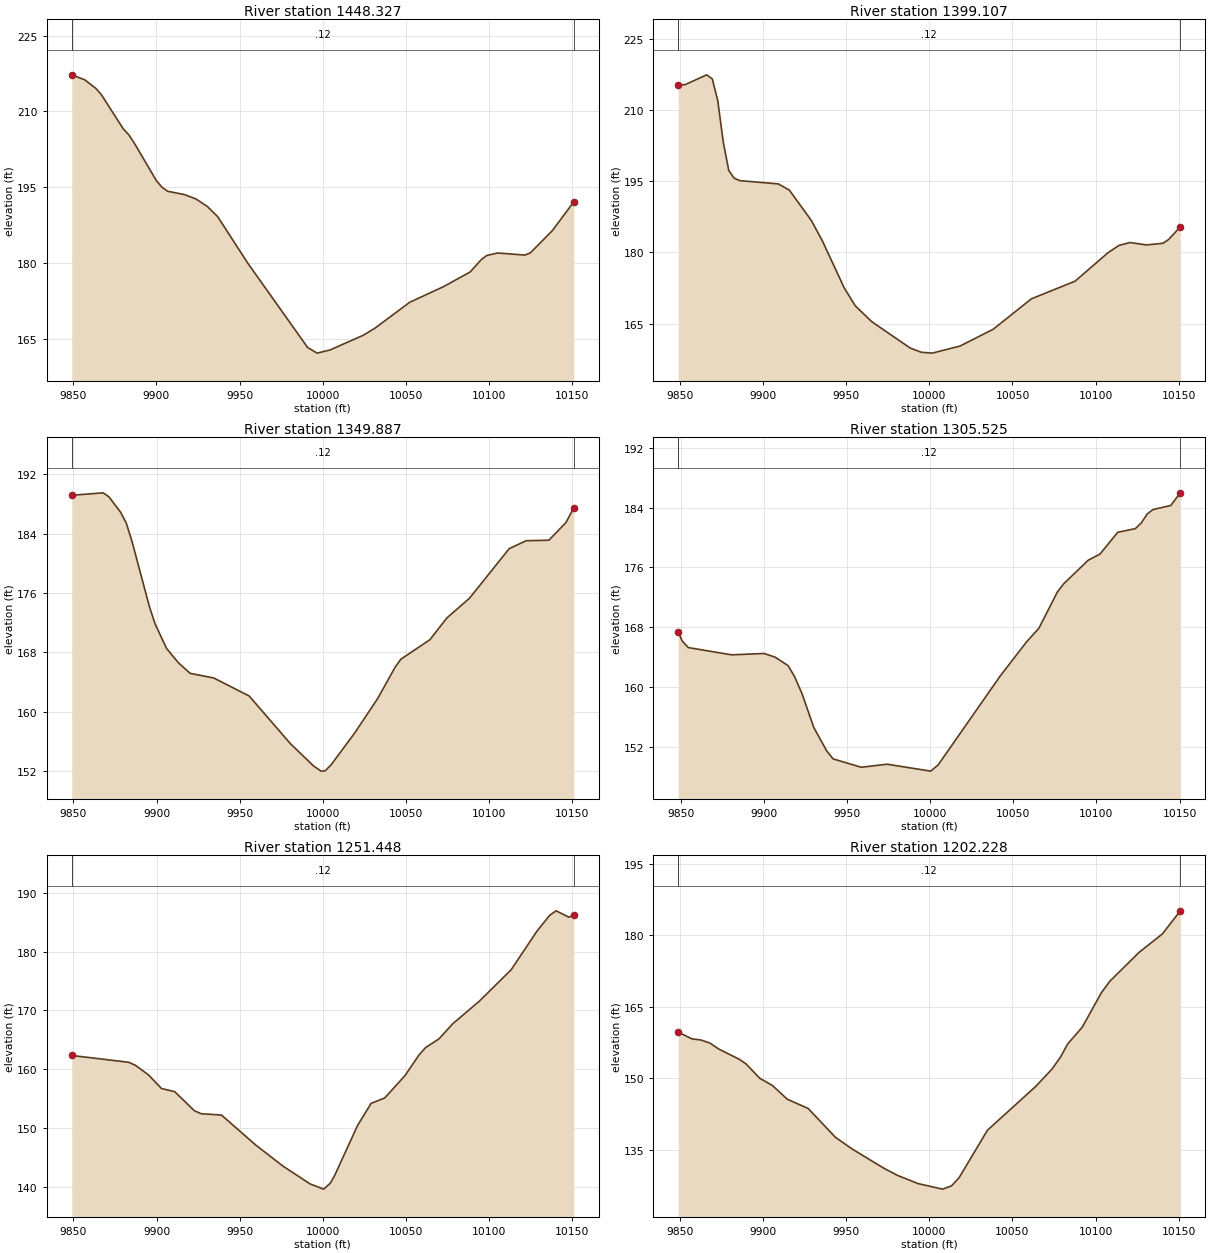
Type RM Length L Ch R = 1 ,1448.327,49.219800,49.219800,49.219800
XS GIS Cut Line= 6
1146489.36517423 846100.835414811146393.71203605846082.324331103
1146327.73955654846043.0286579041146303.35433353846033.739610943
 1146257.2396141846028.4670842411146203.02547655 846032.78106379
#Sta/Elev= 30
9849.135217.21419856.977216.21939863.594214.52749866.903213.29499880.138206.4916
9883.447205.32719886.756 203.671    9900196.25149903.392194.94139906.784 194.158
 9916.96193.49079923.744192.63129930.527191.17279936.861189.11639954.766179.9875
9990.891163.21789996.625162.106510004.35162.735310024.21165.627910031.23167.0255
10052.18172.162210072.67175.2921 10088.6178.189410095.17180.604410098.46181.4297
10105.03181.938410121.45181.520910124.73181.963410137.94186.361110150.86192.0911
#Mann= 3 , 0 , 0
9849.135    0.12       09849.135    0.12       010150.86    0.12       0
#XS Ineff= 2 , 0
       0                               0
Bank Sta=9849.135,10150.86
Exp/Cntr=0.3,0.1

Type RM Length L Ch R = 1 ,1399.107,49.219700,49.219700,49.219700
XS GIS Cut Line= 6
1146511.73067923845992.1492532841146362.95798999846011.118662027
1146358.85483772846011.2905058331146328.07434695846017.233974858
1146257.13519547846019.9701966681146211.97863326846025.404042577
#Sta/Elev= 30
9849.023215.44569852.949215.38719866.178217.48919869.486216.62249872.793212.0424
  9876.1203.29729879.408197.29889882.715195.64469886.023195.16049909.174194.4667
9915.789193.17969929.019186.77289935.634182.48919948.863172.49979955.478168.7368
  9965.4165.39439988.552159.81719995.167 158.93910001.76158.753810018.45160.2441
10038.43163.796910061.41170.220610087.68173.940710107.39179.9294   10114181.4776
10120.61 182.09610130.52181.590210140.43181.928210143.74182.689310150.93185.4011
#Mann= 3 , 0 , 0
9849.023    0.12       09849.023    0.12       010150.93    0.12       0
#XS Ineff= 2 , 0
       0                               0
Bank Sta=9849.023,10150.93
Exp/Cntr=0.3,0.1

Type RM Length L Ch R = 1 ,1349.887,44.361700,44.361700,44.361700
XS GIS Cut Line= 6
1146479.79881974845915.6922661291146424.32682388845934.531044921
 1146352.9932502845964.0310390641146337.63630851845969.181841536
1146282.07318068 845989.922736041146194.84856879846014.587059106
#Sta/Elev= 30
9849.024189.17769867.922189.51369871.387188.97289878.317186.91939881.782185.4412
9885.246182.96789895.641174.23369899.106 171.8489906.036168.53039913.098  166.61
9920.198165.17259934.399164.54939955.701162.11879980.554155.6775 9994.52 152.664
    9999151.987110001.43152.038110004.93152.824810018.94157.060310032.95161.7605
10043.45  165.9910046.96167.082910064.36169.702610074.58172.637410088.22175.3063
10112.09181.988110122.32183.055610135.95183.123710146.18185.497610150.95187.5043
#Mann= 3 , 0 , 0
9849.024    0.12       09849.024    0.12       010150.95    0.12       0
#XS Ineff= 2 , 0
       0                               0
Bank Sta=9849.024,10150.95
Exp/Cntr=0.3,0.1

Type RM Length L Ch R = 1 ,1305.525,54.077800,54.077800,54.077800
XS GIS Cut Line= 6
1146444.29627832845848.4600033581146359.56791085845897.031428168
1146300.28848188845946.2310808631146274.78116383845963.927672857
1146237.94522145845983.244676875  1146187.540025846003.790321842
#Sta/Elev= 30
9848.582167.36349850.932 166.1689854.645165.27869880.637164.30749900.203164.4875
9906.895 163.9949914.628162.86429918.495161.41449923.014159.12169930.095154.5918
9937.828151.47969941.695   150.49958.609149.28079974.174149.689810000.37148.7633
10004.82 149.575 10042.1161.450710058.03 166.04210065.44167.858710076.55172.7072
10080.26173.781810095.08176.954210102.21177.785910112.83180.687710123.46181.1825
10127.01181.936310130.55183.127210134.09183.733510144.72184.270310150.48185.9658
#Mann= 3 , 0 , 0
9848.582    0.12       09848.582    0.12       010150.48    0.12       0
#XS Ineff= 2 , 0
       0                               0
Bank Sta=9848.582,10150.48
Exp/Cntr=0.3,0.1

Type RM Length L Ch R = 1 ,1251.448,49.219700,49.219700,49.219700
XS GIS Cut Line= 6
 1146405.2460134845803.4911242871146343.21892741845844.535246321
1146282.69514347845889.8305568851146281.06984681845890.996065678
1146211.25698224845942.6817921611146157.59140633845975.878572088
#Sta/Elev= 30
9849.026162.34989883.237161.19129887.307 160.6749895.128159.05229903.043156.7157
9910.911156.19549922.713  152.969926.782152.44369939.076152.21099959.565147.1366
9975.957143.54449992.348140.497210000.52139.6125 10004.6140.651610006.97141.8425
10020.93150.450510029.03154.192710037.26155.1283 10049.5 158.94510057.67162.3641
10061.75163.677210069.91165.182510078.08167.726710094.05 171.55910113.33176.9487
10128.77183.490110136.48 186.20510140.34 186.95210148.05185.868210150.97186.2606
#Mann= 3 , 0 , 0
9849.026    0.12       09849.026    0.12       010150.97    0.12       0
#XS Ineff= 2 , 0
       0                               0
Bank Sta=9849.026,10150.97
Exp/Cntr=0.3,0.1

Type RM Length L Ch R = 1 ,1202.228,49.219700,49.219700,49.219700
XS GIS Cut Line= 6
1146372.74175015845758.2339565771146254.01212748845849.832222635
1146252.38683081845850.9977314281146232.27814302845866.119792643
1146172.49610947845919.1908901721146137.44310244845947.204051997
#Sta/Elev= 30
9849.043159.68179857.362158.27019862.733158.03829868.104 157.3949873.475156.1268
9885.604154.02039889.748153.05299898.035150.00719905.701148.4843 9914.61145.6022
9927.186143.65499943.616137.58919954.041135.05679972.622131.12429980.909129.6041
9993.341127.872510007.96126.717910013.41127.408910017.99 129.14510034.98139.0873
10064.04 148.29310073.92151.979810078.87154.436410083.24157.205510092.01160.7378
10103.57168.010410108.67170.412410126.21176.4565 10140.2180.322410150.97185.1712
#Mann= 3 , 0 , 0
9849.043    0.12       09849.043    0.12       010150.97    0.12       0
#XS Ineff= 2 , 0
       0                               0
Bank Sta=9849.043,10150.97
Exp/Cntr=0.3,0.1

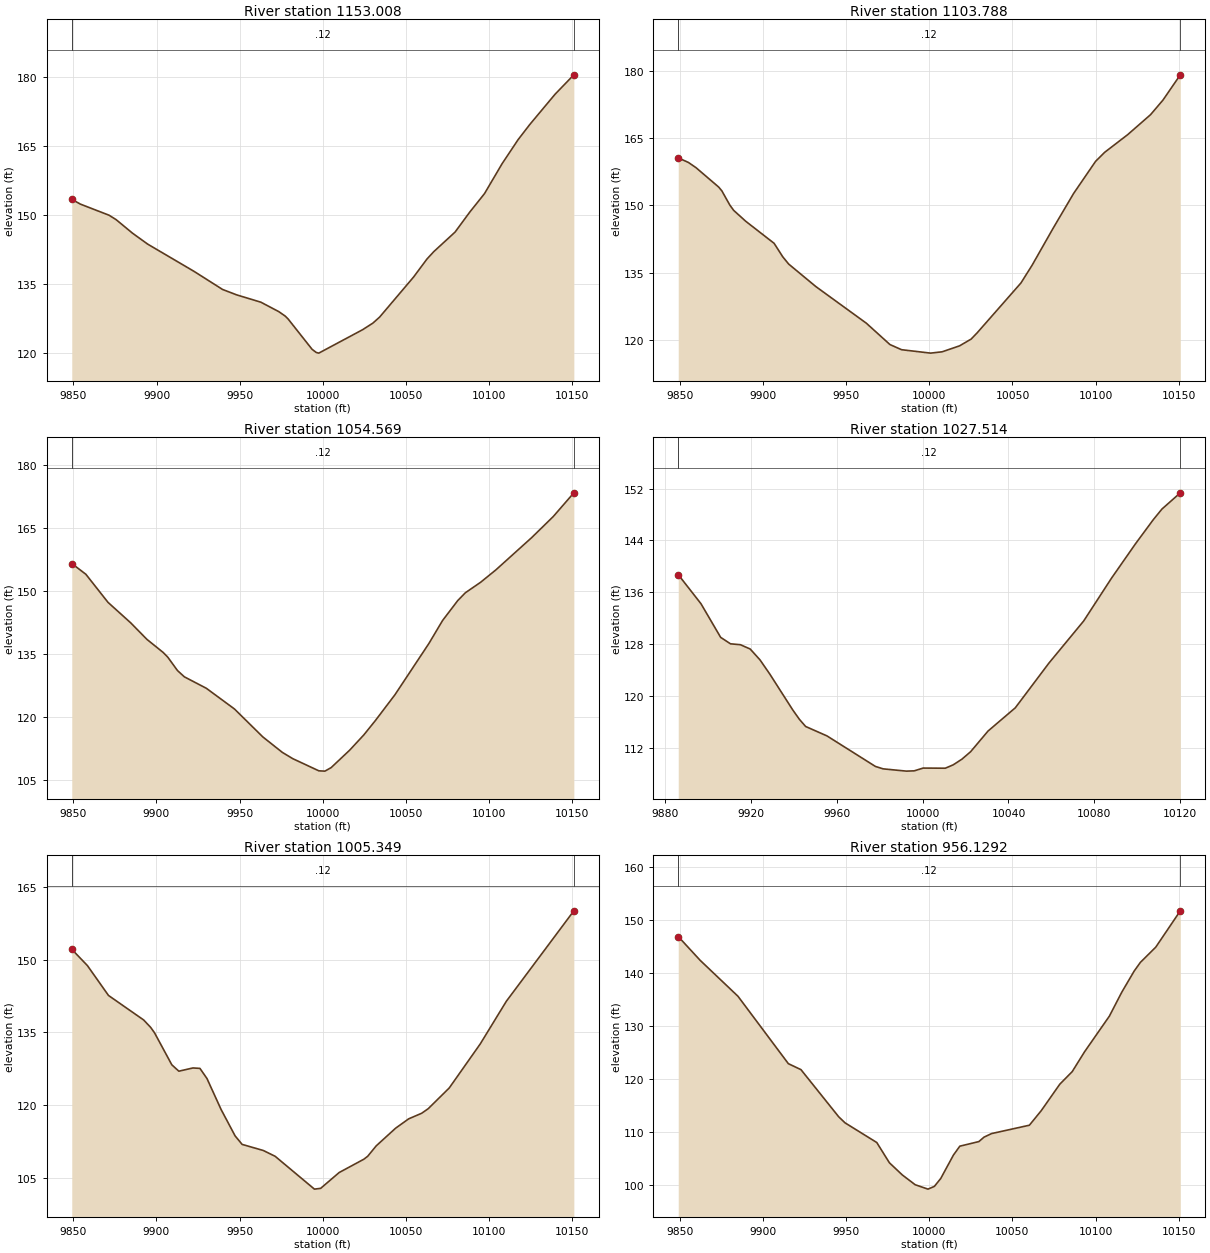
Type RM Length L Ch R = 1 ,1153.008,49.219800,49.219800,49.219800
XS GIS Cut Line= 6
1146321.51175101845703.4717253931146295.22930196845725.792689633
1146264.51110843 845756.972934551146177.02651313845873.142102224
1146148.10438105845905.1247166011146122.24392729845928.794573211
#Sta/Elev= 30
9849.042153.47869854.242152.4298 9871.46 150.0229875.764149.04829885.535146.1283
9894.746143.7303 9922.38137.86989939.722133.89849948.197132.72289962.722131.1366
9973.487129.09159977.413128.10739979.127127.49159993.546120.90119996.048120.2141
 9997.58120.070110023.91125.153510030.09126.582710034.16127.894210054.54136.5789
10062.68 140.52910066.76142.121410079.51146.354510088.36 150.69610097.21 154.704
10107.84 161.23110117.46166.447710124.52169.7502 10139.7176.314710150.95180.5132
#Mann= 3 , 0 , 0
9849.042    0.12       09849.042    0.12       010150.95    0.12       0
#XS Ineff= 2 , 0
       0                               0
Bank Sta=9849.042,10150.95
Exp/Cntr=0.3,0.1

Type RM Length L Ch R = 1 ,1103.788,49.219700,49.219700,49.219700
XS GIS Cut Line= 6
1146259.67748602845673.0693646011146206.18895339845729.828597817
1146187.09491239845762.9664514371146151.13692485845850.432587978
1146123.60662043845886.9401849061146091.46122735845918.218000616
#Sta/Elev= 30
9849.133160.61889855.292159.57549859.818158.42079873.393154.11049875.365153.2373
9880.128150.08229882.444148.89489889.655146.47469906.747  141.549911.957138.5278
9915.488136.91419931.854131.88199962.146123.72139976.384118.94169983.371117.7968
10000.81117.034410007.76117.333310018.19118.657810025.14120.163110028.76121.5547
10055.09 132.689 10061.8136.651510074.45144.915910086.78152.688410099.94159.8293
10105.39161.841410119.22 165.78410132.96170.240910140.44173.503210150.86179.1398
#Mann= 3 , 0 , 0
9849.133    0.12       09849.133    0.12       010150.86    0.12       0
#XS Ineff= 2 , 0
       0                               0
Bank Sta=9849.133,10150.86
Exp/Cntr=0.3,0.1

Type RM Length L Ch R = 1 ,1054.569,27.055000,27.055000,27.055000
XS GIS Cut Line= 6
1146225.39865018845664.0018062961146185.16225244845700.622361574
1146154.74238245845735.7875940291146114.31810874845806.073944132
1146089.90189933845838.846968692 1146032.4264753 845892.65903251
#Sta/Elev= 30
9849.089156.53669857.575153.97029870.883147.29049884.528142.41699894.277 138.484
9903.967135.39329906.748134.28279912.643 131.0679916.778129.57279929.995126.8458
9946.867121.93139963.951115.27419975.698111.5866 9981.94110.10519997.622107.2088
10001.27107.1381   10005  107.9710016.17112.132210024.66115.761110031.51119.1259
10043.34125.2983 10063.8137.523210071.98142.968610081.13147.726110085.71149.5793
10094.88 152.07910104.04155.021910125.65162.732810138.51167.7057 10150.9173.3544
#Mann= 3 , 0 , 0
9849.089    0.12       09849.089    0.12       0 10150.9    0.12       0
#XS Ineff= 2 , 0
       0                               0
Bank Sta=9849.089,10150.9
Exp/Cntr=0.3,0.1

Type RM Length L Ch R = 1 ,1027.514,22.164700,22.164700,22.164700
XS GIS Cut Line= 5
1146187.33680132845686.7318704431146144.85741937845728.143819213
1146133.63383502 845750.991830171146095.07785916845768.892818958
1146008.78591323845831.316779852
#Sta/Elev= 30
9886.219138.7232 9896.81134.23059905.974129.03769910.556128.04149915.138127.9067
9919.719127.24179924.301125.55949928.883123.35889939.529117.84419942.629116.3891
9945.544115.27979955.487113.82449978.027109.11399981.645108.73779992.496108.3885
9996.113 108.43210000.26108.859510010.58108.839410014.28109.361510018.33110.2356
10022.38111.391510030.48114.575910043.17 118.16110058.82125.061110075.02131.5695
10087.96138.167410099.15143.488110107.42 147.20110111.46148.845510120.01  151.35
#Mann= 3 , 0 , 0
9886.219    0.12       09886.219    0.12       010120.01    0.12       0
#XS Ineff= 2 , 0
       0                               0
Bank Sta=9886.219,10120.01
Exp/Cntr=0.3,0.1

Type RM Length L Ch R = 1 ,1005.349,49.219800,49.219800,49.219800
XS GIS Cut Line= 6
1146216.56800002845653.180043278 1146121.7246116845730.333025233
1146097.50227688845743.6546359671146095.68583725845744.491622856
1146066.67606325845760.0082868581145968.55961769845823.861775092
#Sta/Elev= 30
9849.095152.17389858.489148.81259871.177142.63539892.323137.57019896.552136.0316
9898.845134.92659909.243128.3117 9913.47126.98749921.928 127.6579926.157127.5692
9930.387125.47299938.845   119.19947.304 113.6219951.533111.86369964.221 110.611
9971.356109.41279994.993102.62489998.738102.784510009.84106.048610024.72108.8082
   10027109.406310032.17111.574410043.82115.217610051.65117.142710059.48118.2997
10063.39119.236810076.05123.525310094.71132.634110110.36141.424810150.96160.1198
#Mann= 3 , 0 , 0
9849.095    0.12       09849.095    0.12       010150.96    0.12       0
#XS Ineff= 2 , 0
       0                               0
Bank Sta=9849.095,10150.96
Exp/Cntr=0.3,0.1

Type RM Length L Ch R = 1 ,956.1292,49.219700,49.219700,49.219700
XS GIS Cut Line= 6
1146204.33021775845624.002984343 1146109.4926434 845678.68326538
 1146074.9459027845699.866102837 1146073.2526296 845700.93044593
1146042.10464957845719.6484360851145942.07910752845773.597693763
#Sta/Elev= 30
9849.004146.85729862.225142.36549884.948135.60739915.245122.92089922.819121.7974
9945.542 112.9159949.329111.78249968.423108.07589976.024104.26089983.817101.9627
9991.514100.13169999.21299.3020710003.06 99.816910006.89101.301910014.54105.7189
10018.37107.386810029.86108.257110032.94109.090710037.51109.762110060.21111.3342
10067.33114.067410078.51119.057810085.97121.422610093.42125.167810108.33131.8714
10115.79136.380610123.24140.356510126.97141.987810136.24144.862510150.99 151.696
#Mann= 3 , 0 , 0
9849.004    0.12       09849.004    0.12       010150.99    0.12       0
#XS Ineff= 2 , 0
       0                               0
Bank Sta=9849.004,10150.99
Exp/Cntr=0.3,0.1

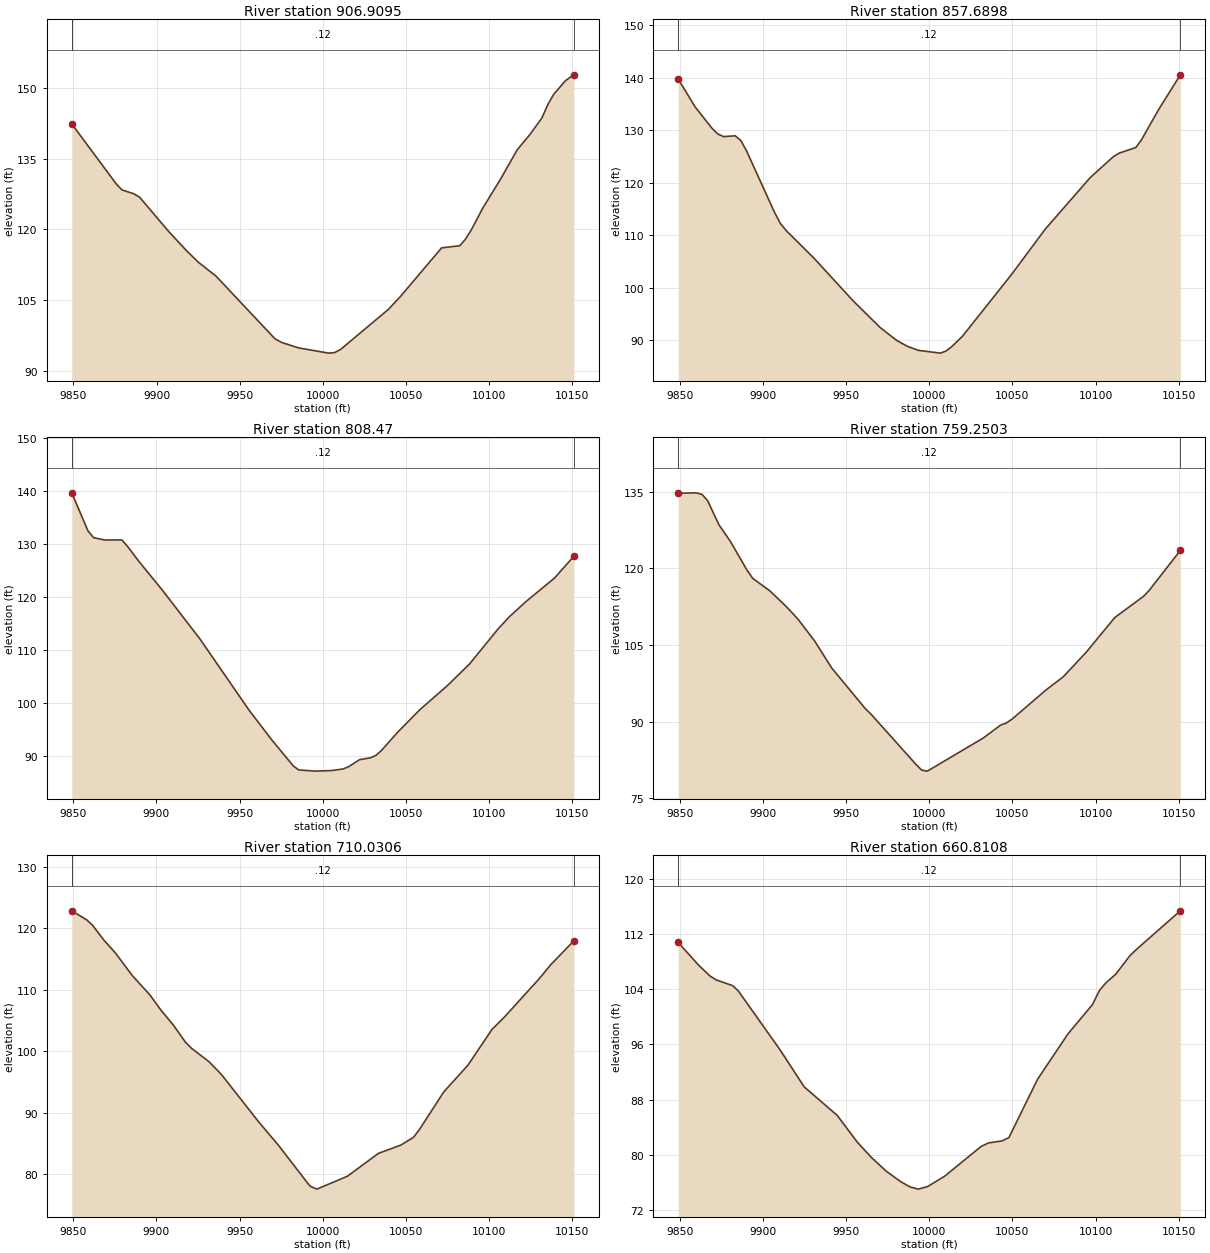
Type RM Length L Ch R = 1 ,906.9095,49.219700,49.219700,49.219700
XS GIS Cut Line= 6
1146188.10782822845601.1971063971146083.01970901845643.132625081
1146049.36279752845658.1129290561146047.52708345845658.906751359
1146004.01418532845678.2905378231145909.34235847845717.216767434
#Sta/Elev= 30
9849.013142.36949875.671129.69469879.203128.37649886.268127.57179889.801126.8327
9907.463119.5006 9918.06115.48529925.125113.05619935.722110.10919971.19496.82509
9975.32596.019949985.55894.8642510003.5193.76409 10007.193.8767910010.6994.54117
10039.42103.0277 10046.6105.737910071.46116.082610082.42116.542710085.65117.8661
 10089.2119.809610096.29124.558610106.93130.671210116.93136.871510124.67 140.168
10131.77143.613810135.31146.440310138.86148.636910145.96151.5475   10151152.7831
#Mann= 3 , 0 , 0
9849.013    0.12       09849.013    0.12       0   10151    0.12       0
#XS Ineff= 2 , 0
       0                               0
Bank Sta=9849.013,10151
Exp/Cntr=0.3,0.1

Type RM Length L Ch R = 1 ,857.6898,49.219800,49.219800,49.219800
XS GIS Cut Line= 6
1146182.74025178845580.8335227811146114.71124935845601.084775948
1146080.86263962845607.1349626191145982.49877833845618.623854364
1145944.78452177845627.179265665 1145888.3826997845643.882354238
#Sta/Elev= 30
9849.026139.78819859.091134.50889869.465130.33619872.923129.27959876.381128.7996
9883.297128.95819886.693128.03429890.087126.09669907.058114.27849910.452 112.253
9913.846110.91449930.622105.63089953.95297.567359970.44292.395879980.33389.94844
9986.92688.79055 9993.5288.0345910006.7187.5093410010.0187.9049410013.3188.68545
10019.9190.7069910049.76102.624610069.89111.213710096.88 121.01510110.57124.9397
10113.99125.624510124.26126.724210127.68128.220310137.94133.956610150.98140.5842
#Mann= 3 , 0 , 0
9849.026    0.12       09849.026    0.12       010150.98    0.12       0
#XS Ineff= 2 , 0
       0                               0
Bank Sta=9849.026,10150.98
Exp/Cntr=0.3,0.1

Type RM Length L Ch R = 1 ,  808.47,49.219700,49.219700,49.219700
XS GIS Cut Line= 6
1146189.16492904845547.6669093241146095.38697282845567.509702586
1146062.28693874845567.0859815351146017.26684025 845559.68792319
1145986.54892394845560.5394797911145892.99728866845583.016597945
#Sta/Elev= 30
9849.106139.6247 9858.84132.45169862.233131.1578 9869.02130.7212  9879.2130.7408
9882.593 129.536 9889.38126.71659903.528121.27499926.171112.04249955.89498.51884
9969.01893.13153  9982.2 88.10729985.52887.337639995.51487.1096710005.5187.22178
10012.1587.5196810015.4787.93022 10022.189.2774810028.6989.6214910031.9790.07926
10035.2591.00596 10045.194.4825710058.2898.6801610074.95103.263810088.28107.3534
10105.23113.889910112.04116.212210122.26119.1443 10139.3123.5465 10150.9127.6493
#Mann= 3 , 0 , 0
9849.106    0.12       09849.106    0.12       0 10150.9    0.12       0
#XS Ineff= 2 , 0
       0                               0
Bank Sta=9849.106,10150.9
Exp/Cntr=0.3,0.1

Type RM Length L Ch R = 1 ,759.2503,49.219700,49.219700,49.219700
XS GIS Cut Line= 5
1146183.75758834845477.3093397131146038.53553861 845514.81955581
1146036.57993378845515.2386139871145989.03423616845527.209325114
1145892.88849339845557.979242572
#Sta/Elev= 30
9849.012134.72329859.925134.80389863.313 134.4919864.422134.09619866.702 133.264
9873.479128.54349880.256125.35419890.421119.6359 9893.81118.04479903.975115.6371
9914.141112.47149920.918110.09919931.084105.75629941.249100.5139 9961.5892.49935
9964.96991.438169992.07781.564999995.46580.474049998.85480.2777910032.6786.80594
10042.82 89.2817 10046.2 89.678610049.5990.4148110070.2596.1894510080.5898.75727
10094.36103.560810111.58110.369410128.81114.513110132.25115.682310150.98  123.52
#Mann= 3 , 0 , 0
9849.012    0.12       09849.012    0.12       010150.98    0.12       0
#XS Ineff= 2 , 0
       0                               0
Bank Sta=9849.012,10150.98
Exp/Cntr=0.3,0.1

Type RM Length L Ch R = 1 ,710.0306,49.219800,49.219800,49.219800
XS GIS Cut Line= 6
 1146155.7006838845407.2263590791146120.00499812845416.991919381
1146080.38055434845433.1670604311146047.52887698845451.064879333
1145972.94475472845498.4220011121145884.82578385845537.096793944
#Sta/Elev= 30
9849.065122.80919858.143121.32699861.544120.46429868.347118.0591 9875.15  116.01
9885.354112.31849895.955109.16479903.042106.5394 9910.13104.24469917.217101.5228
9920.761100.52369931.52998.287499939.00196.216919961.41888.503629973.33184.69284
9991.34578.37664 9992.5278.018189996.438 77.554310014.7879.6427410033.4583.36829
10046.9684.7181510054.5585.97408 10058.287.2742910072.7793.3685810087.3497.72883
10101.84103.558910108.92105.442510130.13111.7668 10137.2114.082910150.97117.9334
#Mann= 3 , 0 , 0
9849.065    0.12       09849.065    0.12       010150.97    0.12       0
#XS Ineff= 2 , 0
       0                               0
Bank Sta=9849.065,10150.97
Exp/Cntr=0.3,0.1

Type RM Length L Ch R = 1 ,660.8108,49.219700,49.219700,49.219700
XS GIS Cut Line= 6
1146116.48034706845362.1365981651146073.01081178845372.968680948
 1146043.0500983845387.4477536191145936.47716969845474.531661579
1145899.05033673845495.9738155461145859.73681849845512.855961741
#Sta/Elev= 30
9849.093110.76929861.503107.44999868.185105.91819871.894105.35289881.819104.5239
9885.253103.73979910.22995.257279924.80589.870159944.67185.735159956.74481.86158
9965.345 79.61299974.09877.666419982.85176.140229988.47175.377039993.42975.06022
    9999 75.433910009.1776.9170510031.1781.23718 10035.581.7415810043.7582.04477
10047.8882.5162510065.16  90.98910083.3597.5162610098.16101.792810102.26103.7972
10106.04104.883810112.19106.197110120.44108.798310124.01109.650810150.93115.3518
#Mann= 3 , 0 , 0
9849.093    0.12       09849.093    0.12       010150.93    0.12       0
#XS Ineff= 2 , 0
       0                               0
Bank Sta=9849.093,10150.93
Exp/Cntr=0.3,0.1