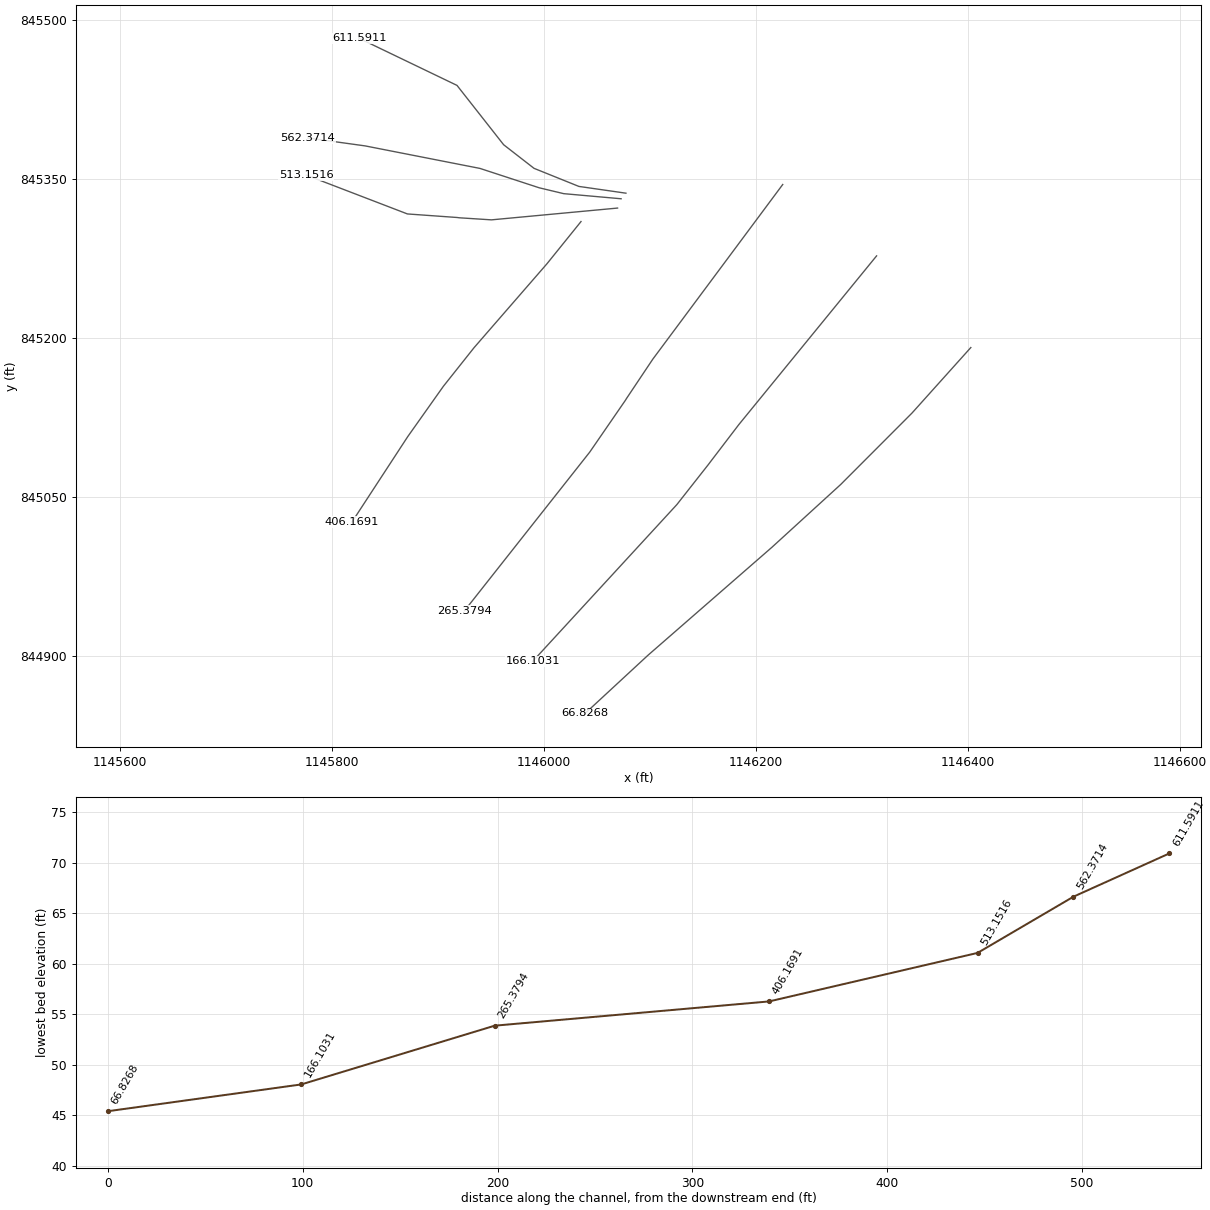
HEC-RAS study 9_ras.prj: 9

--- 9_ras.g01 (geometry) --- (continued)

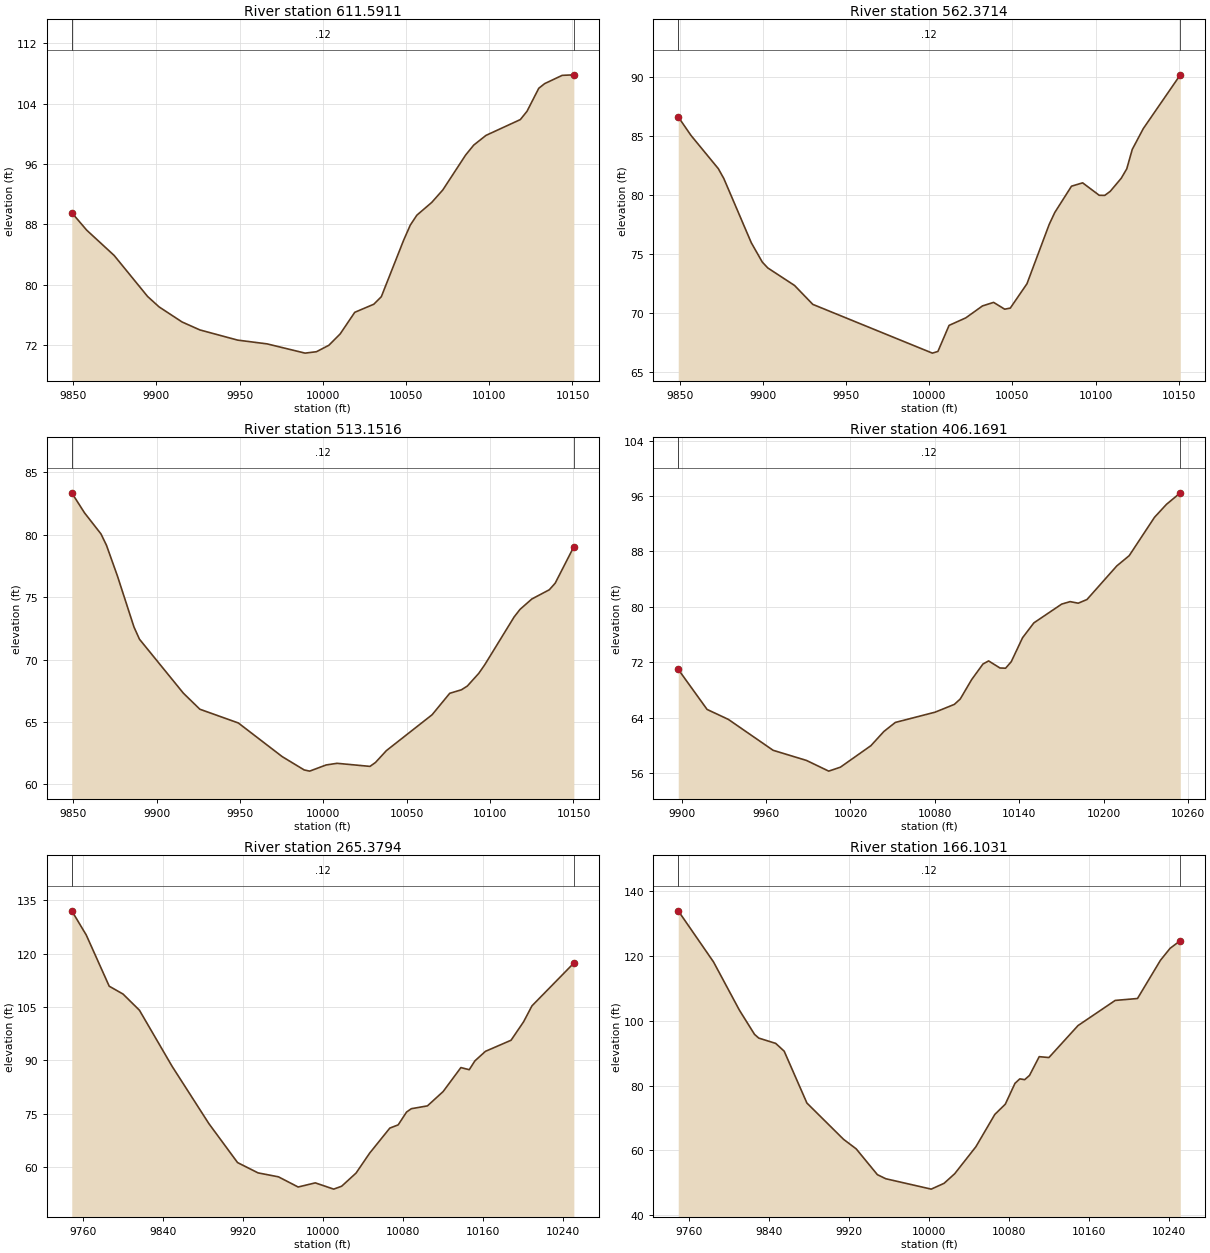
Type RM Length L Ch R = 1 ,611.5911,49.219700,49.219700,49.219700
XS GIS Cut Line= 6
1146077.11676051845336.9327566091146032.75507259 845343.30825817
1145990.43044867 845360.36690556 1145961.7341063845382.651984451
1145917.74712165845438.6262796741145825.46665179845483.025467031
#Sta/Elev= 30
9849.10889.539029858.06187.224849874.57683.866729894.653 78.43279901.57177.04465
9915.40675.041739926.12973.986519948.78872.637149966.48972.138349989.30670.91169
9996.15171.0992210003.5971.9500910010.3973.4568510019.1676.3231410030.6277.39803
10035.1378.3967710048.5885.9102510052.5487.8919210056.4989.2080710065.4390.90036
10072.08 92.5559 10085.897.1875710090.6798.5044110098.0399.7910910118.66101.8869
10122.69102.991110129.73106.033510133.26106.654410143.82107.752110150.82107.8227
#Mann= 3 , 0 , 0
9849.108    0.12       09849.108    0.12       010150.82    0.12       0
#XS Ineff= 2 , 0
       0                               0
Bank Sta=9849.108,10150.82
Exp/Cntr=0.3,0.1

Type RM Length L Ch R = 1 ,562.3714,49.219800,49.219800,49.219800
XS GIS Cut Line= 6
1146072.60760733845331.6592927841146018.45027759 845336.48158924
 1145995.3459387845342.0047497171145939.41549331845360.294304516
1145831.00128124845381.5578093321145777.12790319845389.030653603
#Sta/Elev= 30
9849.068  86.6489856.75785.074539873.18382.259029876.48981.421499893.02375.97736
9899.63774.339789902.94473.845449918.999 72.36479929.98170.7610510001.8866.63007
10005.2266.7738310011.9268.9799810021.9669.61643   1003270.6289410038.6970.92997
10045.3870.3535710048.7370.4459510058.77 72.510410072.1577.54574 10075.5 78.5494
10085.5480.7753410092.2381.0594710102.2180.0049210105.5279.9954510108.8380.33789
10115.4681.4496610118.7782.2459310122.0883.8930210128.7185.6555210150.9790.21171
#Mann= 3 , 0 , 0
9849.068    0.12       09849.068    0.12       010150.97    0.12       0
#XS Ineff= 2 , 0
       0                               0
Bank Sta=9849.068,10150.97
Exp/Cntr=0.3,0.1

Type RM Length L Ch R = 1 ,513.1516,106.982500,106.982500,106.982500
XS GIS Cut Line= 6
1146069.24428368845322.8938325051145950.22916606845311.768824652
1145919.89559227845313.7184190751145917.91473916845313.994500369
1145870.96526524845317.3474901771145775.61405933845353.957078978
#Sta/Elev= 30
 9849.0783.346429856.70481.74601 9866.5980.056379869.88579.148329876.47576.68229
9886.36172.611189889.65671.630489916.01767.305549925.90266.021389948.96864.92226
9975.314 62.22499988.46461.162369991.752 61.066410001.6361.5594110008.2161.69238
10027.9461.4461610031.2361.7590210037.81 62.711910065.2265.5832210075.7767.29674
 10082.867.5786910086.3167.8760510093.21 68.897710096.8569.5988210114.4273.41423
10117.9474.0159810124.9774.8430510135.5175.5870110139.0276.1129610150.2179.03095
#Mann= 3 , 0 , 0
 9849.07    0.12       0 9849.07    0.12       010150.21    0.12       0
#XS Ineff= 2 , 0
       0                               0
Bank Sta=9849.07,10150.21
Exp/Cntr=0.3,0.1

Type RM Length L Ch R = 1 ,406.1691,140.789700,140.789700,140.789700
XS GIS Cut Line= 6
1146034.75457279845310.1774617281146002.60645874845270.326226569
1145933.85696042845191.1942046791145904.92201758845154.772471181
 1145871.2135549845107.1634743331145818.67258727845026.699794772
#Sta/Elev= 30
9897.59170.959969918.11365.17368  9933.263.739829965.05859.273369988.77257.81118
10004.5856.26665 10012.956.83695 10034.659.9451110043.8562.0013110051.9663.29762
10080.2664.7807710093.9265.9034410098.1166.6836910106.2369.4873410114.27 71.7341
10118.2972.1784510126.3371.1600410130.3571.1272710134.3772.0667810142.4175.52714
10150.4577.6725710170.2480.3843410176.2280.74051   10182 80.514710188.2281.04743
10209.43 85.900210218.2287.3746810236.2292.9159210244.6994.7798710254.5796.44994
#Mann= 3 , 0 , 0
9897.591    0.12       09897.591    0.12       010254.57    0.12       0
#XS Ineff= 2 , 0
       0                               0
Bank Sta=9897.591,10254.57
Exp/Cntr=0.3,0.1

Type RM Length L Ch R = 1 ,265.3794,99.276300,99.276300,99.276300
XS GIS Cut Line= 6
 1146225.0659421845345.1288934461146102.46624859845180.311735774
1146077.69568033845143.2629388811146076.65227351845141.556685027
1146043.02014842845092.7053444761145924.88551034844943.054457202
#Sta/Elev= 30
9749.018  131.999763.479125.21579786.461110.8297 9800.28108.62469816.636104.0994
9849.34888.333449886.14872.238439914.77161.319369935.21658.429349955.618 57.3225
9975.35154.462849992.46555.6240210010.9153.8677310018.8854.6902910033.2558.37966
10046.7663.9456510066.9970.9999210075.3571.9054810083.7175.50359 10088.576.44088
10104.6177.2377810120.2781.2508510138.0587.9900210146.41  87.38910152.0489.87125
10162.6392.55283 10188.295.6620510200.74100.8455 10209.1105.314310250.97117.3215
#Mann= 3 , 0 , 0
9749.018    0.12       09749.018    0.12       010250.97    0.12       0
#XS Ineff= 2 , 0
       0                               0
Bank Sta=9749.018,10250.97
Exp/Cntr=0.3,0.1

Type RM Length L Ch R = 1 ,166.1031,99.276300,99.276300,99.276300
XS GIS Cut Line= 6
1146313.60863459845277.7804953071146183.68123426  845118.6383375
1146156.65000112845083.2362545031146155.45754875845081.630621497
1146125.15152826845043.0982930781145989.12323863844895.188774505
#Sta/Elev= 30
9749.014133.89559784.286118.13539810.225103.22919825.28895.795729829.52394.64287
9846.465 93.00549854.93690.603759877.66674.603399914.23163.433269926.93760.47417
9948.11452.515419956.53151.2555910001.9348.0545410014.77 49.844410025.3852.79273
10046.6161.1302910065.5271.0978510075.9974.2491510085.6880.6869210090.5382.06754
10095.3781.8179910100.2283.1353910109.9188.9108610119.6188.6447210148.6998.49926
10185.87 106.25910208.16106.851610231.08118.632810240.77122.335910250.97124.6905
#Mann= 3 , 0 , 0
9749.014    0.12       09749.014    0.12       010250.97    0.12       0
#XS Ineff= 2 , 0
       0                               0
Bank Sta=9749.014,10250.97
Exp/Cntr=0.3,0.1

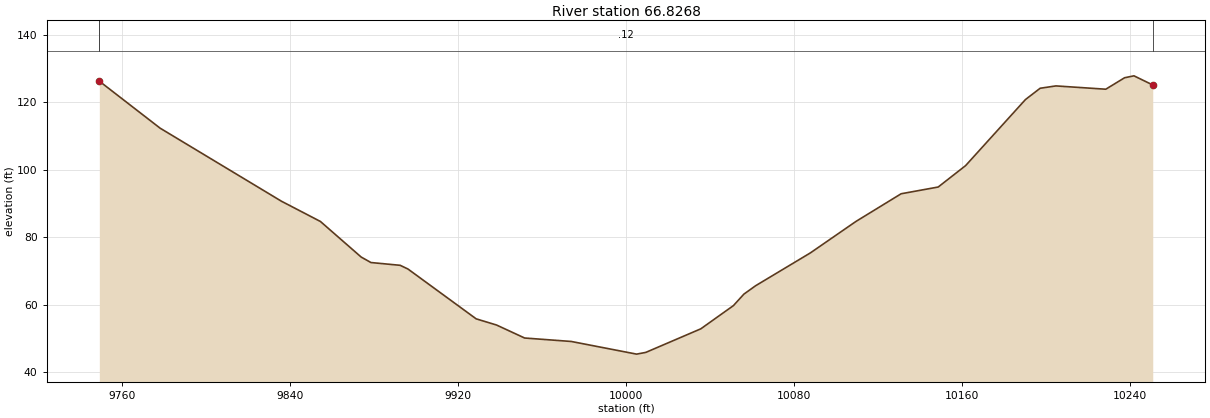
Type RM Length L Ch R = 1 , 66.8268,0.000000,0.000000,0.000000
XS GIS Cut Line= 6
1146402.51166289845191.2820902051146347.05836845845129.530943587
1146279.65814739845062.0044330711146214.82969202845002.825223953
1146097.90017928844900.9536509541146038.65702627844846.146106175
#Sta/Elev= 30
9749.023126.25669777.979112.3353 9835.83 90.68439854.37284.698149873.79174.15869
9878.436 72.53449892.36871.711579896.091 70.61129928.59255.854489938.30854.02188
9951.67750.176739973.92149.1498110005.0345.4031910009.4345.9149410035.6252.89285
10051.1859.7746710056.1763.1759510061.7365.6512310087.8375.3776410109.5984.71674
10131.0992.9011710148.7594.8990610161.81 101.23610190.34120.809710197.33124.1519
10204.84124.847410228.62123.870510237.56127.261310242.03127.836310250.99125.1349
#Mann= 3 , 0 , 0
9749.023    0.12       09749.023    0.12       010250.99    0.12       0
#XS Ineff= 2 , 0
       0                               0
Bank Sta=9749.023,10250.99
Exp/Cntr=0.3,0.1